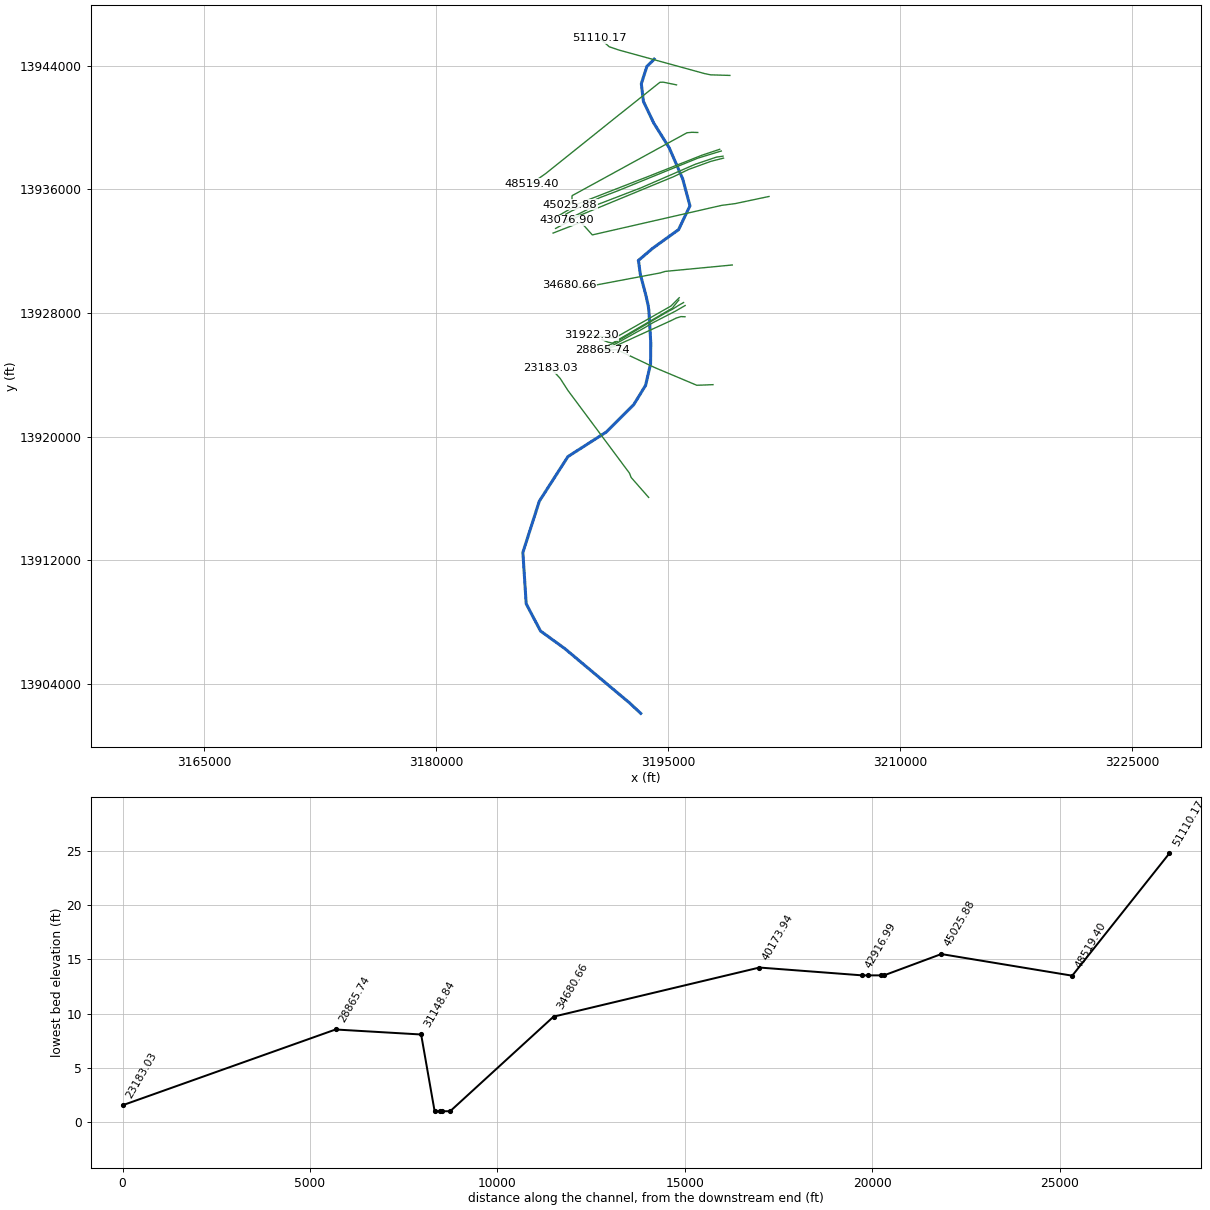
--- G103-00-00LH.prj (project) ---

Proj Title=G103-00-00LH
Current Plan=p02
Default Exp/Contr=.3,.1
English Units
Geom File=g02
Flow File=f02
Flow File=f01
Plan File=p01
Plan File=p02
Y Axis Title=Elevation
X Axis Title(PF)=Main Channel Distance
X Axis Title(XS)=Station
BEGIN DESCRIPTION:
San Jacinto River Watershed
Lake Houston
HCFCD unit G103-00-00
(Flood Hazard, Floodway)Model
10, 2, 1, 0.2% Event
Filename G1030000lh.prj
Prepared by:  FTN Associates Ltd.   DATE:  February 2003
Reviewed by:     DATE:
STATUS (Final)
The boundary condition is known water surface elevation at the downstream end, obtained from the existing FIS HEC-2 data. WSEL of 45.44, 47.84, 48.84, 51.84 are used for the 10, 50, 100 and 500yr profiles respectively. The geometry for the cross-sections (except for 51138.74) are based upon the effective FIS HEC-2 (9/10/87) data adjusted for subsidence.
Section 51110.17 is located at the same location as East Fork San Jacinto 411v45, so the survey data are used in that section.
Section 48519.40 is located at the same location as West Fork San Jacinto RS 44044.71 (lh8p67), so the survey data are used in that section.
END DESCRIPTION:
DSS Export Rating Curves= 0
DSS Export Rating Curve Sorted= 0
DSS Export Volume Flow Curves= 0
DXF OffsetX= 0
DXF OffsetY= 0
DXF ScaleX= 1
DXF ScaleY= 10

--- G103-00-00LH.p02 (plan) ---

Plan Title=Floodway
Version=Version 3.0.1  Mar 2001
Short Identifier=Floodway0607
Geom File=g02
Flow File=f02
Subcritical Flow
K Sum by GR= 0
Std Step Tol= 0.003
Critical Tol= 0.003
Num of Std Step Trials= 20
Max Error Tol= 0.1
Flow Tol Ratio= 0.001
Split Flow NTrial= 30
Split Flow Tol= 0.02
Split Flow Ratio= 0.02
Log Output Level= 0
Friction Slope Method= 1
Unsteady Friction Slope Method= 2
Parabolic Critical Depth
Global Vel Dist= 0 , 0 , 0
Global Log Level= 0
CheckData=True
Encroach Param=-1 ,0,0, 2
Encroach River=G103-00-00LH
Encroach Reach=G1030000LH_0001
Encroach Node=51110.17
       1    1461 7241.44
Encroach Node=48519.40
       1    138710107.83
Encroach Node=45025.88
       1  617.52 9017.52
Encroach Node=43497.52
       1    1841 9843.77
Encroach Node=43408.39
       1 1721.25 9033.39
Encroach Node=43243
       1    1839 9033.84
Encroach Node=43076.90
       1    1839 9033.84
Encroach Node=42916.99
       1    1783    9518
Encroach Node=40173.94
       1    3096   11000
Encroach Node=34680.66
       1  876.88 9254.88
Encroach Node=31922.30
       1  823.12 5006.97
Encroach Node=31712.46
       1 1076.33    4971
Encroach Node=31684
       1    1060 4958.33
Encroach Node=31655.28
       1 1095.33 4958.33
Encroach Node=31508.32
       1  600.55    4717
Encroach Node=31148.84
       1  487.48 4705.48
Encroach Node=28865.74
       1    1299 6414.83
Encroach Node=23183.03
       1 1965.76 9046.76
Encroach Node=21163.64
       1  674.46 6369.46
Encroach Node=14422.44
       1  795.09 6939.09
Encroach Node=13380.19
       1  779.95    8026
Encroach Node=10988.99
       1     760 8000.28
Encroach Node=5802.974
       1    199510416.14
Encroach Node=2497.772
       1 2829.9212279.92
Encroach Node=216.724
       1  816.16 7816.16
Encroach Node=106.780
       1  620.23 7620.23
Computation Interval=1HOUR
Output Interval=1HOUR
Run HTab= 0
Run UNet= 0
Run PostProcess= 0
UNET Theta= 1
UNET ZTol= 0.02
UNET ZSATol= 0.1
UNET MxIter= 20
UNET MaxInSteps= 20
UNET DtIC= 0
UNET DtMin= 0
UNET MaxCRTS= 20
UNET WFStab= 2
UNET SFStab= 1
UNET WFX= 1
UNET SFX= 1
UNET Convert EG Bridges=-1
UNET Use Existing IB Tables=-1
Instantaneous Interval=1HOUR
Write IC File= 0
IC Time=0
Write Velocity= 0
Write Detailed= 0

--- G103-00-00LH.p01 (plan) ---

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Plan Title=FEMA Effective June 2007
Short Identifier=FEMAeff0607
Geom File=g02
Flow File=f01
DSS File=dss

--- G103-00-00LH.f02 (steady flow) ---

Flow Title=Floodway
Version=Version 3.0.1  Mar 2001
Number of Profiles= 2
Profile Names=1PCT_100yr, 1PCTFloodway_100yrFW
River Rch & RM=G103-00-00LH,G1030000LH_0001 ,51110.17
  121724  121724
River Rch & RM=G103-00-00LH,G1030000LH_0001 ,48519.40
  214619  214619
River Rch & RM=G103-00-00LH,G1030000LH_0001 ,43497.52
  219709  219709
River Rch & RM=G103-00-00LH,G1030000LH_0001 ,43408.39
  220520  220520
River Rch & RM=G103-00-00LH,G1030000LH_0001 ,40173.94
  229864  229864
River Rch & RM=G103-00-00LH,G1030000LH_0001 ,34680.66
  245600  245600
River Rch & RM=G103-00-00LH,G1030000LH_0001 ,31922.30
  245635  245635
River Rch & RM=G103-00-00LH,G1030000LH_0001 ,31712.46
  245637  245637
River Rch & RM=G103-00-00LH,G1030000LH_0001 ,31655.28
  245637  245637
River Rch & RM=G103-00-00LH,G1030000LH_0001 ,31508.32
  245639  245639
River Rch & RM=G103-00-00LH,G1030000LH_0001 ,31148.84
  245645  245645
River Rch & RM=G103-00-00LH,G1030000LH_0001 ,28865.74
  245681  245681
River Rch & RM=G103-00-00LH,G1030000LH_0001 ,23183.03
  245755  245755
River Rch & RM=G103-00-00LH,G1030000LH_0001 ,21163.64
  245789  245789
River Rch & RM=G103-00-00LH,G1030000LH_0001 ,14422.44
  245892  245892
River Rch & RM=G103-00-00LH,G1030000LH_0001 ,13380.19
  245912  245912
River Rch & RM=G103-00-00LH,G1030000LH_0001 ,10988.99
  245944  245944
River Rch & RM=G103-00-00LH,G1030000LH_0001 ,5802.974
  246013  246013
River Rch & RM=G103-00-00LH,G1030000LH_0001 ,2497.772
  246064  246064
River Rch & RM=G103-00-00LH,G1030000LH_0001 ,216.724
  246099  246099
River Rch & RM=G103-00-00LH,G1030000LH_0001 ,106.780
  246100  246100
Boundary for River Rch & Prof#=G103-00-00LH,G1030000LH_0001 , 1
Up Type= 0
Dn Type= 1
Dn Known WS=48.84
Boundary for River Rch & Prof#=G103-00-00LH,G1030000LH_0001 , 2
Up Type= 0
Dn Type= 1
Dn Known WS=49.84
DSS Import GetInterval= 0
DSS Import GetPeak= 0
DSS Import FillOption= 0

--- G103-00-00LH.f01 (steady flow) ---

Flow Title=FEMA Effective June 2007
Version=Version 3.0.1  Mar 2001
Number of Profiles= 4
Profile Names=10PCT_10yr, 2PCT_50yr, 1PCT_100yr, 0.2PCT_500yr
River Rch & RM=G103-00-00LH,G1030000LH_0001 ,51110.17
   42935   94300  121724  211500
River Rch & RM=G103-00-00LH,G1030000LH_0001 ,48519.40
   75056  160681  214619  369116
River Rch & RM=G103-00-00LH,G1030000LH_0001 ,43497.52
   76526  163871  219709  375554
River Rch & RM=G103-00-00LH,G1030000LH_0001 ,43408.39
   76760  164380  220520  376580
River Rch & RM=G103-00-00LH,G1030000LH_0001 ,40173.94
   79457  170236  229864  388397
River Rch & RM=G103-00-00LH,G1030000LH_0001 ,34680.66
   84000  180100  245600  408300
River Rch & RM=G103-00-00LH,G1030000LH_0001 ,31922.30
   83888  180106  245635  408411
River Rch & RM=G103-00-00LH,G1030000LH_0001 ,31712.46
   83883  180107  245637  408417
River Rch & RM=G103-00-00LH,G1030000LH_0001 ,31655.28
   83881  180107  245637  408419
River Rch & RM=G103-00-00LH,G1030000LH_0001 ,31508.32
   83876  180108  245639  408424
River Rch & RM=G103-00-00LH,G1030000LH_0001 ,31148.84
   83856  180109  245645  408444
River Rch & RM=G103-00-00LH,G1030000LH_0001 ,28865.74
   83740  180116  245681  408560
River Rch & RM=G103-00-00LH,G1030000LH_0001 ,23183.03
   83505  180131  245755  408795
River Rch & RM=G103-00-00LH,G1030000LH_0001 ,21163.64
   83394  180138  245789  408906
River Rch & RM=G103-00-00LH,G1030000LH_0001 ,14422.44
   83066  180158  245892  409234
River Rch & RM=G103-00-00LH,G1030000LH_0001 ,13380.19
   83033  180162  245912  409297
River Rch & RM=G103-00-00LH,G1030000LH_0001 ,10988.99
   82900  180169  245944  409400
River Rch & RM=G103-00-00LH,G1030000LH_0001 ,5802.974
   82678  180183  246013  409622
River Rch & RM=G103-00-00LH,G1030000LH_0001 ,2497.772
   82516  180193  246064  409784
River Rch & RM=G103-00-00LH,G1030000LH_0001 ,216.724
   82402  180199  246099  409897
River Rch & RM=G103-00-00LH,G1030000LH_0001 ,106.780
   82400  180200  246100  409900
Boundary for River Rch & Prof#=G103-00-00LH,G1030000LH_0001 , 1
Up Type= 0
Dn Type= 1
Dn Known WS=45.44
Boundary for River Rch & Prof#=G103-00-00LH,G1030000LH_0001 , 2
Up Type= 0
Dn Type= 1
Dn Known WS=47.84
Boundary for River Rch & Prof#=G103-00-00LH,G1030000LH_0001 , 3
Up Type= 0
Dn Type= 1
Dn Known WS=48.84
Boundary for River Rch & Prof#=G103-00-00LH,G1030000LH_0001 , 4
Up Type= 0
Dn Type= 1
Dn Known WS=51.84
DSS Import GetInterval= 0
DSS Import GetPeak= 0
DSS Import FillOption= 0

--- G103-00-00LH.g02 (geometry) ---

Geom Title=G103-00-00LH June 2007
Version=Version 3.0.1  Mar 2001

River Reach=G103-00-00LH ,G1030000LH_0001
Reach XY= 30
     3194095.382    13944421.703     3194030.746    13944347.267
     3193624.925    13943955.934     3193263.117    13942833.672
     3193396.985    13941695.793     3194066.325    13940290.179
     3195070.336    13938683.762     3195940.478    13936675.741
     3196409.017    13934935.456     3195672.742    13933395.973
     3193999.391     13932191.16     3193065.566    13931396.303
        3193088.       13931329.        3193200.       13930501.
      3193550.75       13929180.      3193699.75       13928524.
        3193752.       13928166.        3193875.       13926054.
        3193860.       13924711.      3193539.25       13923323.
       3192769.5       13922071.        3190996.       13920304.
      3188517.75       13918717.       3186664.5       13915830.
        3185602.       13912517.        3185816.       13909194.
      3186741.75       13907436.       3188324.5       13906287.
        3192517.       13902769.        3193225.       13902106.

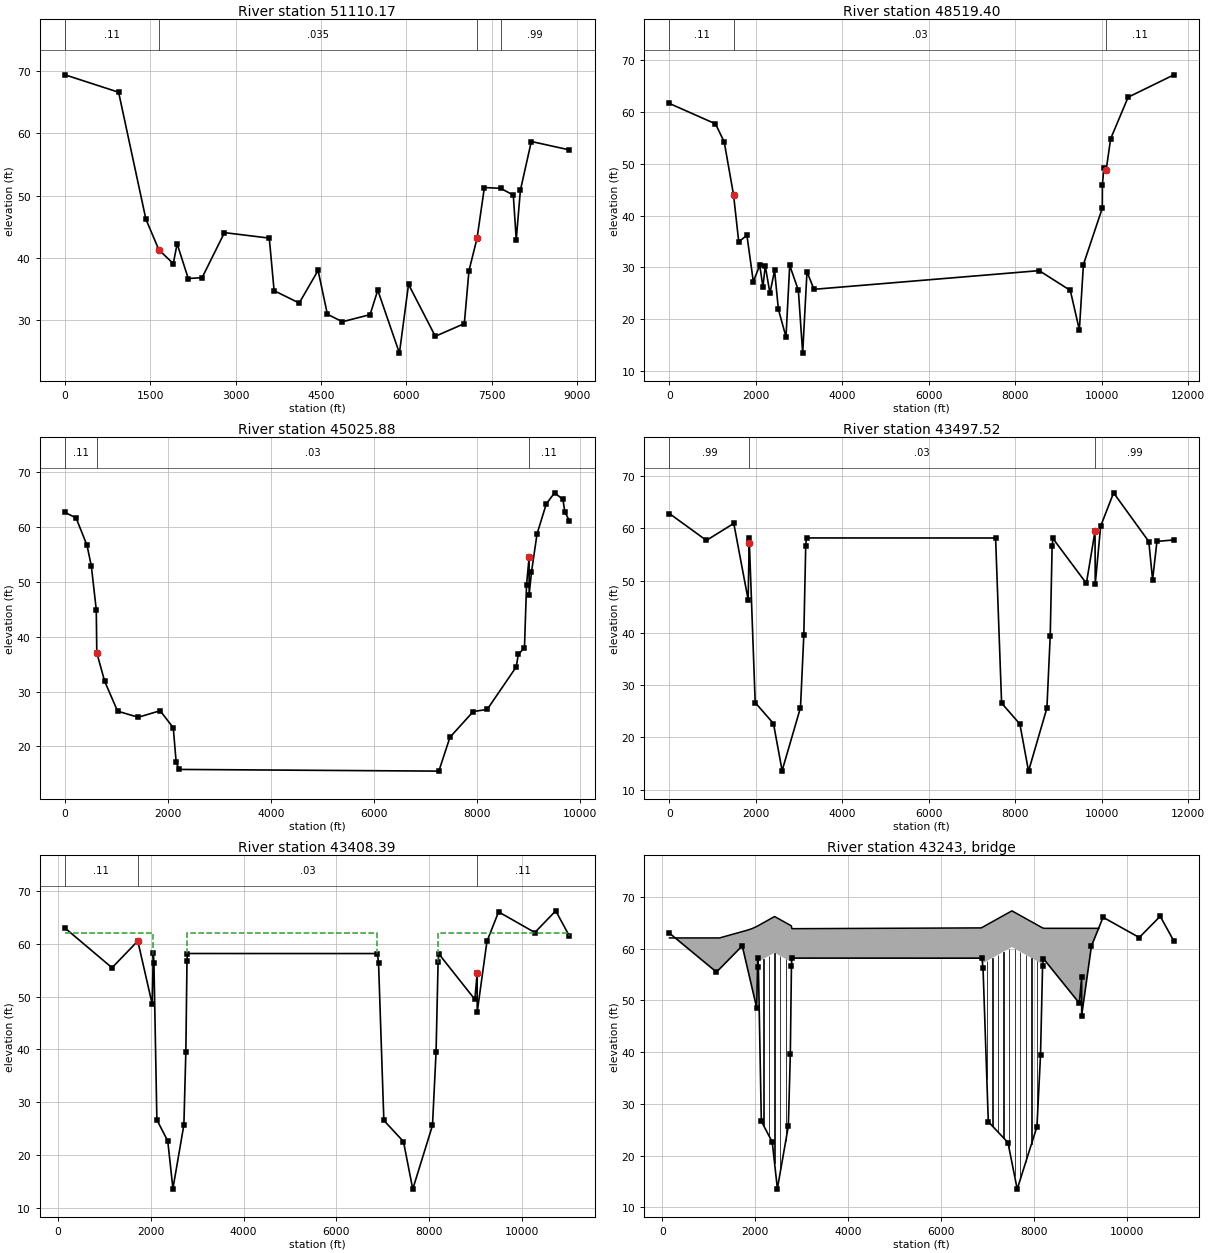
Type RM Length L Ch R = 1 ,51110.17,1982.44,2590.77,8825.41
BEGIN DESCRIPTION:
cross section 411v45 of EF San Jacincto and cross section lh9p25 of Lake Houston are located at the same place. Hence cross section 411v45, being a surveyed cross section is used at this location.
411v45
This is a common section for EF San jacincto and Lake Houston. The boundary condition is applied based on the WSELs obtained at this cross section from the Lake Houston model
Bank Station offset =      -877
END DESCRIPTION:
XS GIS Cut Line= 6
     3198991.102    13943369.938     3197746.983    13943408.545
     3197355.319    13943489.579     3191804.499    13945015.717
     3191187.013    13945224.865     3190584.124    13945769.748
#Sta/Elev= 30
       0   69.36  941.98   66.57 1421.32   46.22 1649.12   41.31 1902.72   39.09
 1970.34   42.27 2166.07    36.7 2409.52   36.84 2802.27   44.06 3590.06   43.18
 3674.79   34.75 4115.96   32.77 4448.14      38 4610.96   30.98 4874.73   29.77
 5361.49   30.91 5496.89   34.83  5877.3   24.74 6037.54   35.77 6507.63   27.44
 7017.81   29.47 7099.32   37.94 7241.44   43.15 7370.81   51.29 7658.04   51.16
 7878.97   50.07 7930.38   42.95 8003.35   50.85 8195.34   58.67 8866.25   57.32
#Mann= 4 ,-1 , 0
       0     .11       0 1649.12    .035       0 7241.44     .11       0
 7658.04     .99       0
Bank Sta=1649.12,7241.44
XS Rating Curve= 0
Exp/Cntr=.3,.1

Type RM Length L Ch R = 1 ,48519.40,3605.53,3493.51,2321.7
BEGIN DESCRIPTION:
lh8p67
Bank Station offset =     18517
Section 48519.40 is a common section to West Fork San Jacinto RS 44044.71 (lh8p67), so the survey data are used in that section.
END DESCRIPTION:
XS GIS Cut Line= 6
     3195539.716    13942759.906     3194677.891    13942935.463
     3194467.725    13942927.962     3191748.696     13940765.22
     3187065.105    13937014.407     3186155.401    13936376.018
#Sta/Elev= 30
       0   61.58 1064.14   57.66 1267.01   54.18 1482.83   43.98 1602.83   34.96
 1792.83   36.16 1940.83   27.25 2088.83   30.44 2162.83   26.24 2216.83   30.33
 2324.83   25.03 2432.83   29.42 2520.83   21.92 2696.83   16.61 2782.83    30.4
 2982.83    25.6 3082.83   13.49 3182.83   29.19 3342.83   25.78 8556.83   29.38
 9276.83   25.57 9486.83   17.96 9580.83   30.5610017.83   41.4310019.83   45.83
10052.83   49.2210107.83   48.8210210.78   54.7810615.13   62.7911675.83    67.1
#Mann= 3 , 0 , 0
       0     .11       0 1482.83     .03       010107.83     .11       0
Bank Sta=1482.83,10107.83
XS Rating Curve= 0
Exp/Cntr=.3,.1

Type RM Length L Ch R = 1 ,45025.88,1595.79,1528.37,773.36
BEGIN DESCRIPTION:
lh7p61
Bank Station offset =     19382
END DESCRIPTION:
XS GIS Cut Line= 6
     3196912.252     13939679.68     3196529.639     13939691.24
     3196214.717    13939661.122     3188783.585    13935591.268
     3188772.795    13935226.918     3188629.158    13935003.482
#Sta/Elev= 30
       0   62.68   215.2   61.68  427.66   56.67  510.96   52.92  607.24   44.94
  617.52   37.05  771.52   31.84 1021.52   26.42 1423.52   25.31 1847.52    26.5
 2103.52    23.4 2159.52   17.09 2215.52   15.79 7263.52   15.48 7479.52   21.66
 7931.52   26.35 8203.52   26.74 8767.52    34.5 8807.52    36.8 8927.52   37.98
 8967.52   49.48 9017.52   54.47 9017.76    47.6 9062.93   51.76 9171.78   58.76
 9350.67   64.23 9511.99   66.26 9674.29   65.05 9712.21   62.78 9801.91   61.13
#Mann= 3 , 0 , 0
       0     .11       0  617.52     .03       0 9017.52     .11       0
Bank Sta=617.52,9017.52
XS Rating Curve= 0
Exp/Cntr=.3,.1

Type RM Length L Ch R = 1 ,43497.52,82.38,89.13,192.26
BEGIN DESCRIPTION:
lh7p4026 - xs 4/4 at structure
Bank Station offset =     18156
contraction/expansion .5/.7 for section 4/4 due to drastic change in flow area (due to "divided channel" in HEC-2 model)
END DESCRIPTION:
XS GIS Cut Line= 6
     3198332.529    13938592.147     3197188.463    13938210.791
     3193839.312    13936886.019     3188935.499     13934976.63
     3188698.284     13934758.52      3187594.36    13934116.237
#Sta/Elev= 30
       0   62.84  854.25   57.71 1487.83   60.96 1819.41   46.35 1843.77   57.26
 1843.77   58.26 1982.77   26.65 2405.77   22.63 2605.77   13.62 3030.77   25.69
 3107.77   39.59 3151.77   56.68 3169.77   58.18 7543.77   58.17 7682.77   26.55
 8105.77   22.53 8305.77   13.52 8730.77    25.6 8807.77   39.49 8851.77   56.59
 8869.77   58.08 9643.77   49.48 9843.77   59.47 9849.01   49.36 9974.28   60.43
10273.13   66.8211087.81   57.49 11175.4   50.1611276.33   57.5211669.45    57.8
#Mann= 3 , 0 , 0
       0     .99       0 1843.77     .03       0 9843.77     .99       0
Bank Sta=1843.77,9843.77
XS Rating Curve= 0
Exp/Cntr=.7,.5

Type RM Length L Ch R = 1 ,43408.39,320.91,331.49,343.93
BEGIN DESCRIPTION:
lh7p3932 - xs 3/4 at structure
Bank Station offset =     18098
contraction/expansion .5/.7 for section 3/4 due to drastic change in flow area (due to "divided channel" in HEC-2 model)
END DESCRIPTION:
XS GIS Cut Line= 6
     3198436.687    13938482.796     3196925.706    13938021.549
     3191740.655    13935906.176     3190611.396    13935476.739
     3188718.693    13934586.056 3188380.2963617 13934394.788107
#Sta/Elev= 30
  153.34      63 1166.42   55.48 1721.25   60.55 2031.82   48.59  2055.3   58.26
 2069.18   56.46 2132.45   26.65 2367.21   22.63 2478.21   13.62 2714.09   25.69
 2756.82   39.59 2781.24   56.68 2791.23   58.18 6883.39   58.17 6908.39   56.36
 7022.39   26.55 7445.39   22.53 7645.39   13.52 8070.39    25.6 8147.39   39.49
 8191.39   56.59 8209.39   58.08 8983.39   49.48 9033.39   54.48 9033.59   47.07
 9243.96   60.48 9494.27   66.0710275.37   62.1610725.84   66.2711021.93   61.45
#Mann= 3 , 0 , 0
  153.34     .11       0 1721.25     .03       0 9033.39     .11       0
#XS Ineff= 3 ,-1
  153.34 2058.34   62.08 2791.23 6870.95   62.08 8191.0411021.93   62.08
Permanent Ineff=
       F       F       F
Bank Sta=1721.25,9033.39
XS Rating Curve= 0
Exp/Cntr=.7,.5

Type RM Length L Ch R = 3 ,43243   ,,,
BEGIN DESCRIPTION:
FM 1960; contraction/expansion .5/.7 for sections 1/4 to 4/4 due to drastic change in flow area (due to "divided channel" in HEC-2 model)
END DESCRIPTION:
Bridge Culvert--1,0,-1,-1, 0
Deck Dist Width WeirC Skew NumUp NumDn MinLoCord MaxHiCord MaxSubmerge Is_Ogee
107.25,117,2.6,0, 33, 32, , , .95, 0, 0,0,,
  153.34 1231.34 1331.34 1431.34 1531.34 1631.34 1731.34 1831.34 1931.34 2031.34
 2058.34 2178.34 2298.34 2418.34 2538.34 2658.34 2778.34 2791.23 6870.95 6990.95
 7110.95 7230.95 7350.95 7470.95 7530.95 7590.95 7710.95 7830.95 7950.95 8070.95
 8190.95 8231.34 9403.34
   62.08   62.08   62.33   62.58   62.83   63.08   63.33   63.58   63.88   64.29
   64.42   65.02   65.62   66.22   65.62   65.02   64.42   63.87   64.02   64.62
   65.22   65.82   66.42   67.02   67.32   67.02   66.42   65.82   65.22   64.62
   64.02   63.94   63.94
                                                                                
   57.42   58.02   58.62   59.22   58.62   58.02   57.42   57.42   57.02   57.62
   58.22   58.82   59.42   60.02   60.32   60.02   59.42   58.82   58.22   57.62
   57.02
       0  1236.3  1336.3  1436.3  1536.3  1636.3  1736.3  1836.3  1936.3  2036.3
  2063.3  2183.3  2303.3  2423.3  2543.3  2663.3  2783.3 2791.22 6875.91 6995.91
 7115.91 7235.91 7355.91 7475.91 7535.91 7595.91 7715.91 7835.91 7955.91 8075.91
 8195.91   10000
   62.08   62.08   62.33   62.58   62.83   63.08   63.33   63.58   63.88   64.29
   64.42   65.02   65.62   66.22   65.62   65.02   64.42   63.87   64.02   64.62
   65.22   65.82   66.42   67.02   67.32   67.02   66.42   65.82   65.22   64.62
   64.02   63.94
                                                                                
   57.42   58.02   58.62   59.22   58.62   58.02   57.42   57.42   57.02   57.62
   58.22   58.82   59.42   60.02   60.32   60.02   59.42   58.82   58.22   57.62
   57.02
Pier Skew, UpSta & Num, DnSta & Num=  ,2178.34, 6 ,2183.3, 6 , 5 , 5 , 0 ,,
       8       8       6       6     7.5     7.5
     -40      40      40      52      52      65
       8       8       6       6     7.5     7.5
     -40      40      40      52      52      65
Pier Skew, UpSta & Num, DnSta & Num=  ,2298.34, 6 ,2303.3, 6 , 5 , 5 , 0 ,,
       8       8       6       6     7.5     7.5
     -40      40      40      52      52      65
       8       8       6       6     7.5     7.5
     -40      40      40      52      52      65
Pier Skew, UpSta & Num, DnSta & Num=  ,2418.34, 6 ,2423.3, 6 , 5 , 5 , 0 ,,
       8       8       6       6     7.5     7.5
     -40      40      40      52      52      65
       8       8       6       6     7.5     7.5
     -40      40      40      52      52      65
Pier Skew, UpSta & Num, DnSta & Num=  ,2538.34, 6 ,2543.3, 6 , 5 , 5 , 0 ,,
       8       8       6       6     7.5     7.5
     -40      40      40      52      52      65
       8       8       6       6     7.5     7.5
     -40      40      40      52      52      65
Pier Skew, UpSta & Num, DnSta & Num=  ,2658.34, 6 ,2663.3, 6 , 5 , 5 , 0 ,,
       8       8       6       6     7.5     7.5
     -40      40      40      52      52      65
       8       8       6       6     7.5     7.5
     -40      40      40      52      52      65
Pier Skew, UpSta & Num, DnSta & Num=  ,6990.95, 6 ,6995.91, 6 , 5 , 5 , 0 ,,
       8       8       6       6     7.5     7.5
     -40      40      40      52      52      65
       8       8       6       6     7.5     7.5
     -40      40      40      52      52      65
Pier Skew, UpSta & Num, DnSta & Num=  ,7110.95, 6 ,7115.91, 6 , 5 , 5 , 0 ,,
       8       8       6       6     7.5     7.5
     -40      40      40      52      52      65
       8       8       6       6     7.5     7.5
     -40      40      40      52      52      65
Pier Skew, UpSta & Num, DnSta & Num=  ,7230.95, 6 ,7235.91, 6 , 5 , 5 , 0 ,,
       8       8       6       6     7.5     7.5
     -40      40      40      52      52      65
       8       8       6       6     7.5     7.5
     -40      40      40      52      52      65
Pier Skew, UpSta & Num, DnSta & Num=  ,7350.95, 6 ,7355.91, 6 , 5 , 5 , 0 ,,
       8       8       6       6     7.5     7.5
     -40      40      40      52      52      65
       8       8       6       6     7.5     7.5
     -40      40      40      52      52      65
Pier Skew, UpSta & Num, DnSta & Num=  ,7470.95, 6 ,7475.91, 6 , 5 , 5 , 0 ,,
       8       8       6       6     7.5     7.5
     -40      40      40      52      52      65
       8       8       6       6     7.5     7.5
     -40      40      40      52      52      65
Pier Skew, UpSta & Num, DnSta & Num=  ,7590.95, 6 ,7595.91, 6 , 5 , 5 , 0 ,,
       8       8       6       6     7.5     7.5
     -40      40      40      52      52      65
       8       8       6       6     7.5     7.5
     -40      40      40      52      52      65
Pier Skew, UpSta & Num, DnSta & Num=  ,7710.95, 6 ,7715.91, 6 , 5 , 5 , 0 ,,
       8       8       6       6     7.5     7.5
     -40      40      40      52      52      65
       8       8       6       6     7.5     7.5
     -40      40      40      52      52      65
Pier Skew, UpSta & Num, DnSta & Num=  ,7830.95, 6 ,7835.91, 6 , 5 , 5 , 0 ,,
       8       8       6       6     7.5     7.5
     -40      40      40      52      52      65
       8       8       6       6     7.5     7.5
     -40      40      40      52      52      65
Pier Skew, UpSta & Num, DnSta & Num=  ,7950.95, 6 ,7955.91, 6 , 5 , 5 , 0 ,,
       8       8       6       6     7.5     7.5
     -40      40      40      52      52      65
       8       8       6       6     7.5     7.5
     -40      40      40      52      52      65
Pier Skew, UpSta & Num, DnSta & Num=  ,8070.95, 6 ,8075.91, 6 , 5 , 5 , 0 ,,
       8       8       6       6     7.5     7.5
     -40      40      40      52      52      65
       8       8       6       6     7.5     7.5
     -40      40      40      52      52      65
BR Coef=-1 , 0 , 0 ,, 0 ,,,.8,-1,,0,
WSPro=,,,, 1 ,,,, 0 ,,,, 0 ,,,,-1 ,-1 ,-1 , 0 , 0 , 0 , 0 , 0
BC Design=,, 0 ,, 0 ,,,,,,

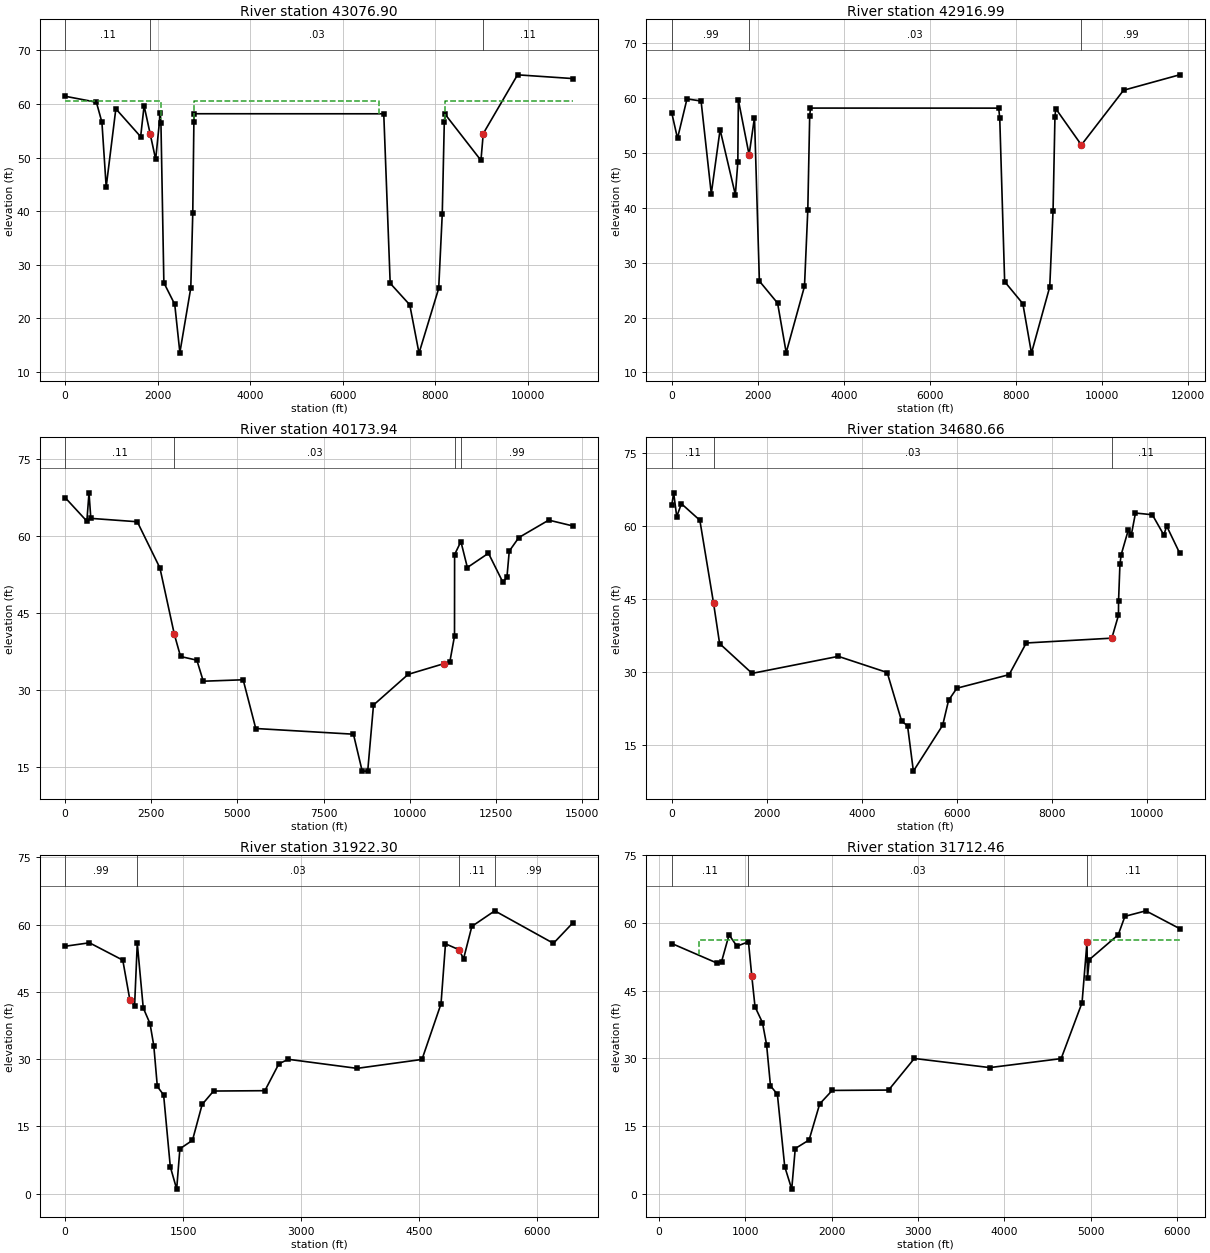
Type RM Length L Ch R = 1 ,43076.90,136.09,159.91,202.88
BEGIN DESCRIPTION:
lh7p379 - xs 2/4 at structure
Bank Station offset =     17945
contraction/expansion .5/.7 for section 2/4 due to drastic change in flow area (due to "divided channel" in HEC-2 model)
END DESCRIPTION:
XS GIS Cut Line= 6
     3198548.022     13938148.79     3198118.585    13938085.169
      3196750.75    13937623.923     3193235.731    13936097.037
      3190341.01    13934983.682 3188419.755405713934010.5652952
#Sta/Elev= 30
       0   61.44  674.41   60.33   793.9   56.59  886.13   44.53 1094.81    59.1
 1630.79    53.9  1705.3   59.67    1839   54.32  1955.3   49.66  2055.3   58.26
 2069.18   56.46 2132.45   26.65 2367.21   22.63 2478.21   13.62 2714.09   25.69
 2756.82   39.59 2781.24   56.68 2791.23   58.18 6883.84   58.17 7022.84   26.55
 7445.84   22.53 7645.84   13.52 8070.84    25.6 8147.84   39.49 8191.84   56.59
 8209.84   58.08 8983.84   49.48 9033.84   54.48 9774.47   65.4410970.92   64.74
#Mann= 3 , 0 , 0
       0     .11       0    1839     .03       0 9033.84     .11       0
#XS Ineff= 3 ,-1
       0  2063.3    60.5 2784.75 6785.91    60.5  8196.810970.92    60.5
Permanent Ineff=
       F       F       F
Bank Sta=1839,9033.84
XS Rating Curve= 0
Exp/Cntr=.7,.5

Type RM Length L Ch R = 1 ,42916.99,2794.65,2743.05,1699.59
BEGIN DESCRIPTION:
lh7p37 - xs 1/4 at structure
Bank Station offset =     18104
contraction/expansion .5/.7 for section 1/4 due to drastic change in flow area (due to "divided channel" in HEC-2 model)
END DESCRIPTION:
XS GIS Cut Line= 6
     3198579.832    13938021.549     3197768.674    13937814.783
     3196321.313    13937289.916     3195367.009    13936828.669
     3189354.896     13934347.48     3187716.675    13933472.701
#Sta/Elev= 30
       0   57.24  131.76   52.65   352.5   59.86  679.69   59.46  916.62   42.57
 1121.43   54.25 1476.23   42.38 1533.69   48.33 1545.79   59.67 1795.79   49.66
 1920.79   56.46 2034.79   26.65 2457.79   22.63 2657.79   13.62 3082.79   25.69
 3159.79   39.59 3203.79   56.68 3221.79   58.18 7595.79   58.17 7620.79   56.36
 7734.79   26.55 8157.79   22.53 8357.79   13.52 8782.79    25.6 8859.79   39.49
 8903.79   56.59 8921.79   58.08    9518   51.46 10498.4   61.43 11799.9   64.24
#Mann= 3 , 0 , 0
       0     .99       0 1795.79     .03       0    9518     .99       0
Bank Sta=1795.79,9518
XS Rating Curve= 0
Exp/Cntr=.7,.5

Type RM Length L Ch R = 1 ,40173.94,4154.9,5493.27,3391.45
BEGIN DESCRIPTION:
lh6p99
Bank Station offset =     16881
channel reach length > LOB and ROB reach length due to the channel sinuosity
END DESCRIPTION:
XS GIS Cut Line= 6
     3201523.873    13935541.302     3199336.097    13935079.662
     3198451.268    13934964.093     3190091.572    13933054.558
     3189360.639    13933875.381     3187554.218    13933172.884
#Sta/Elev= 30
       0   67.56  629.48   62.97  691.86    68.5  744.62   63.52 2093.64   62.86
 2750.74   53.85 3169.25   40.91 3349.25   36.59 3823.25   35.87 4009.25   31.77
 5167.25   32.05 5533.25   22.55 8369.25   21.44 8623.25   14.24 8783.25   14.24
 8951.25   27.13 9958.25   33.11   11000    35.211169.25    35.611303.25   40.58
 11306.1   56.4711488.86      5911676.55   53.9412288.88   56.7212704.25   51.11
12824.73   52.01 12892.9   57.1413171.02   59.7814038.79   63.1814740.68   62.04
#Mann= 4 ,-1 , 0
       0     .11       0 3169.25     .03       011303.25     .11       0
11488.86     .99       0
Bank Sta=3169.25,11000
XS Rating Curve= 0
Exp/Cntr=.3,.1

Type RM Length L Ch R = 1 ,34680.66,3134.68,2758.37,3819.85
BEGIN DESCRIPTION:
lh6p35
Bank Station offset =     19295
500 yr profile not extending, hence no block applied at the edge of xsection on ROB
The flow lines contract d/s of this cross section to allow for the contraction at the structure. hence both ROB and LOB reach lengths > channel reach length
END DESCRIPTION:
XS GIS Cut Line= 6
     3199146.612    13931109.311     3194805.569    13930694.358
     3194486.854    13930596.053     3190264.409    13929800.475
     3189395.224    13929641.017     3188613.198    13929832.533
#Sta/Elev= 30
       0   64.28   38.37   66.75  102.97   61.87  201.15   64.52  589.37   61.13
  876.88   44.18 1004.88   35.86 1687.88   29.75 3501.88   33.24 4529.88   29.93
 4834.88   19.93 4957.88   19.03 5080.88    9.72 5696.88   19.12 5820.88   24.22
 5994.88   26.71 7094.88   29.49 7454.88   35.98 9254.88   36.97 9394.88   41.66
 9396.88   44.65 9425.66   52.13 9452.19   54.08 9603.41   59.19 9664.49    58.1
 9752.43   62.6110107.17   62.2610349.48    58.110408.79   59.9410679.93   54.44
#Mann= 3 , 0 , 0
       0     .11       0  876.88     .03       0 9254.88     .11       0
Bank Sta=876.88,9254.88
XS Rating Curve= 0
Exp/Cntr=.3,.1

Type RM Length L Ch R = 1 ,31922.30,187.45,209.84,214.42
BEGIN DESCRIPTION:
lh5p907 - xs 4/4 at structure
Bank Station offset =     19083
END DESCRIPTION:
XS GIS Cut Line= 6
     3195714.839    13928989.582     3195178.829    13928453.572
     3191527.262    13926376.534     3190801.415    13926477.036
      3190533.41    13926488.203     3190042.068    13926566.371
#Sta/Elev= 30
       0    55.2  308.65   55.97  732.56    52.1  823.12   43.19  882.87   41.96
  916.97   55.85  992.97   41.44 1078.97   37.94 1126.97   33.03 1171.97   23.93
 1251.97   22.03 1336.97    6.02 1417.97    1.02 1458.97   10.02 1618.97   11.91
 1741.97   19.91 1886.97    22.9 2539.97   22.98 2717.97   28.98 2837.97   29.98
 3711.97   27.96 4537.97   29.95 4779.97   42.35 4836.97   55.74 5006.97   54.44
 5067.18   52.43 5172.18   59.63 5463.75    63.1 6209.87   55.85 6457.54   60.43
#Mann= 4 ,-1 , 0
       0     .99       0  916.97     .03       0 5006.97     .11       0
 5463.75     .99       0
Bank Sta=823.12,5006.97
XS Rating Curve= 0
Exp/Cntr=.5,.3

Type RM Length L Ch R = 1 ,31712.46,49.58,57.18,58.87
BEGIN DESCRIPTION:
lh5p887 - xs 3/4 at structure
Bank Station offset =     19427
Cross setion extended on LOB
END DESCRIPTION:
XS GIS Cut Line= 6
 3195689.722830913928841.3814572     3195359.422    13928437.681
     3195286.229    13928327.494     3191398.439    13926057.371
     3191094.145    13926122.454      3190714.36    13926283.132
#Sta/Elev= 30
  151.09   55.46  668.88   51.17  726.88   51.44  813.74    57.4  904.36   54.87
 1038.33   55.85 1076.33   48.34 1114.33   41.44 1200.33   37.94 1248.33   33.03
 1293.33   23.93 1373.33   22.03 1458.33    6.02 1539.33    1.02 1580.33   10.02
 1740.33   11.91 1863.33   19.91 2008.33    22.9 2661.33   22.98 2959.33   29.98
 3833.33   27.96 4659.33   29.95 4901.33   42.35 4958.33   55.74 4964.64   47.92
 4984.81   51.88 5320.47   57.41 5397.87   61.49 5640.29   62.71 6030.57   58.78
#Mann= 3 ,-1 , 0
  151.09     .11       0 1038.33     .03       0 4958.33     .11       0
#XS Ineff= 2 , 0
  465.09 1015.09    56.3 4958.29  465.09    56.3
Permanent Ineff=
       F       F
Bank Sta=1076.33,4958.33
XS Rating Curve= 0
Exp/Cntr=.5,.3

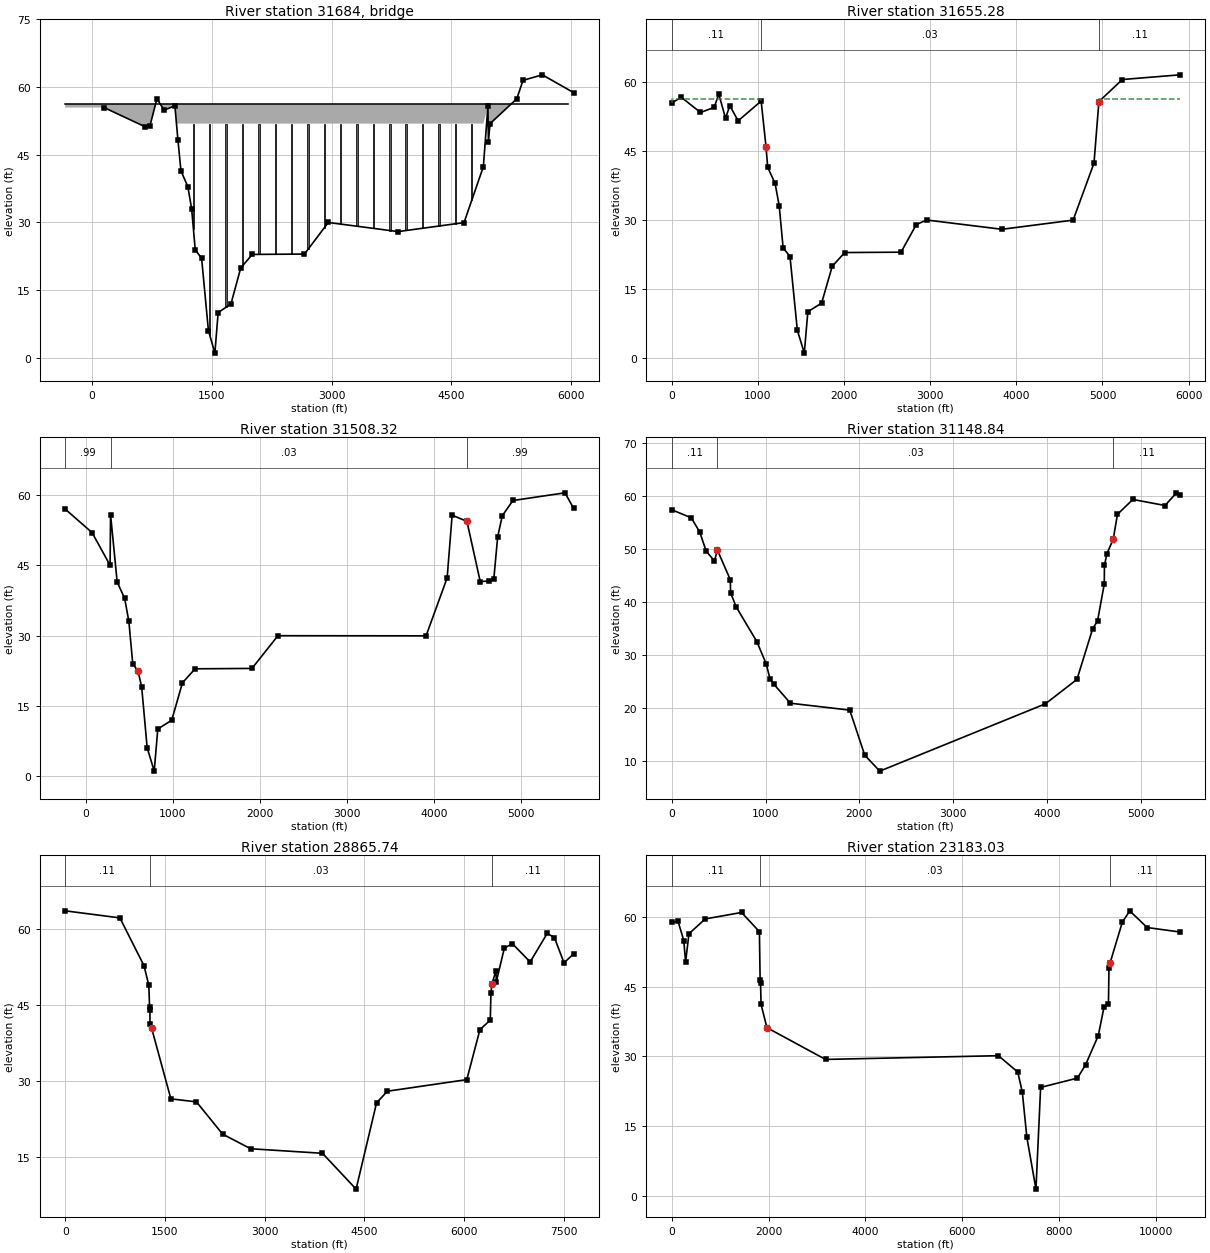
Type RM Length L Ch R = 3 ,31684   ,,,
BEGIN DESCRIPTION:
Union Pacific RR
Bridge width not specified in HEC-2 data and hence measured from MRSids
END DESCRIPTION:
Bridge Culvert--1,0,-1,-1, 0
Deck Dist Width WeirC Skew NumUp NumDn MinLoCord MaxHiCord MaxSubmerge Is_Ogee
16,25,2.6,0, 9, 8, , , .95, 0, 0,0,,
 -334.91  465.09 1064.09 1065.09 2373.09 3090.09 4958.09 4958.59 5965.09
    56.3    56.3    56.3    56.3    56.3    56.3    56.3    56.3    56.3
                            51.9    51.9    51.9    51.9
       0    1064    1065    2624    3340    4958    4959    5500
    56.3    56.3    56.3    56.3    56.3    56.3    56.3    56.3
                    51.9    51.9    51.9    51.9
Pier Skew, UpSta & Num, DnSta & Num=  ,1270.09, 2 ,1275, 2 , 0 , 0 , 0 ,,
      18      18
      35      55
      18      18
      35      55
Pier Skew, UpSta & Num, DnSta & Num=  ,1475.09, 2 ,1485, 2 , 0 , 0 , 0 ,,
      18      18
      35      55
      18      18
      35      55
Pier Skew, UpSta & Num, DnSta & Num=  ,1680.09, 2 ,1695, 2 , 0 , 0 , 0 ,,
      18      18
      35      55
      18      18
      35      55
Pier Skew, UpSta & Num, DnSta & Num=  ,1885.09, 2 ,1905, 2 , 0 , 0 , 0 ,,
      18      18
      35      55
      18      18
      35      55
Pier Skew, UpSta & Num, DnSta & Num=  ,2090.09, 2 ,2115, 2 , 0 , 0 , 0 ,,
      18      18
      35      55
      18      18
      35      55
Pier Skew, UpSta & Num, DnSta & Num=  ,2295.09, 2 ,2325, 2 , 0 , 0 , 0 ,,
      18      18
      35      55
      18      18
      35      55
Pier Skew, UpSta & Num, DnSta & Num=  ,2500.09, 2 ,2535, 2 , 0 , 0 , 0 ,,
      18      18
      35      55
      18      18
      35      55
Pier Skew, UpSta & Num, DnSta & Num=  ,2705.09, 2 ,2745, 2 , 0 , 0 , 0 ,,
      18      18
      35      55
      18      18
      35      55
Pier Skew, UpSta & Num, DnSta & Num=  ,2910.09, 2 ,3375, 2 , 0 , 0 , 0 ,,
      18      18
      35      55
      18      18
      35      55
Pier Skew, UpSta & Num, DnSta & Num=  ,3115.09, 2 ,2955, 2 , 0 , 0 , 0 ,,
      18      18
      35      55
      18      18
      35      55
Pier Skew, UpSta & Num, DnSta & Num=  ,3320.09, 2 ,3585, 2 , 0 , 0 , 0 ,,
      18      18
      35      55
      18      18
      35      55
Pier Skew, UpSta & Num, DnSta & Num=  ,3525.09, 2 ,3165, 2 , 0 , 0 , 0 ,,
      18      18
      35      55
      18      18
      35      55
Pier Skew, UpSta & Num, DnSta & Num=  ,3730.09, 2 ,3795, 2 , 0 , 0 , 0 ,,
      18      18
      35      55
      18      18
      35      55
Pier Skew, UpSta & Num, DnSta & Num=  ,3935.09, 2 ,4005, 2 , 0 , 0 , 0 ,,
      18      18
      35      55
      18      18
      35      55
Pier Skew, UpSta & Num, DnSta & Num=  ,4140.09, 2 ,4215, 2 , 0 , 0 , 0 ,,
      18      18
      35      55
      18      18
      35      55
Pier Skew, UpSta & Num, DnSta & Num=  ,4345.09, 2 ,4425, 2 , 0 , 0 , 0 ,,
      18      18
      35      55
      18      18
      35      55
Pier Skew, UpSta & Num, DnSta & Num=  ,4550.09, 2 ,4635, 2 , 0 , 0 , 0 ,,
      18      18
      35      55
      18      18
      35      55
Pier Skew, UpSta & Num, DnSta & Num=  ,4755.09, 2 ,4845, 2 , 0 , 0 , 0 ,,
      18      18
      35      55
      18      18
      35      55
BR Coef=-1 , 0 , 0 ,, 0 ,,,.8,-1,,0,
WSPro=,,,, 1 ,,,, 0 ,,,, 0 ,,,,-1 ,-1 ,-1 , 0 , 0 , 0 , 0 , 0
BC Design=,, 0 ,, 0 ,,,,,,

Type RM Length L Ch R = 1 ,31655.28,213.98,146.96,87.85
BEGIN DESCRIPTION:
lh5p88 - xs 2/4 at structure
Bank Station offset =     18962
END DESCRIPTION:
XS GIS Cut Line= 6
     3195997.983    13928680.557     3195657.595    13928487.364
     3195280.408    13928248.172     3194936.607    13928071.891
     3191681.653    13926150.858     3190864.193    13925785.148
#Sta/Elev= 30
       0   55.44   111.5   56.68  334.41   53.37  492.57   54.47  547.18   57.34
   624.9   52.14  675.24   54.84  771.26   51.55 1038.33   55.85 1095.33   45.84
 1114.33   41.44 1200.33   37.94 1248.33   33.03 1293.33   23.93 1373.33   22.03
 1458.33    6.02 1539.33    1.02 1580.33   10.02 1740.33   11.91 1863.33   19.91
 2008.33    22.9 2661.33   22.98 2839.33   28.98 2959.33   29.98 3833.33   27.96
 4659.33   29.95 4901.33   42.35 4958.33   55.74  5230.7   60.54 5899.58   61.56
#Mann= 3 ,-1 , 0
       0     .11       0 1038.33     .03       0 4958.33     .11       0
#XS Ineff= 2 , 0
       0    1037    56.3    4958       0    56.3
Permanent Ineff=
       F       F
Bank Sta=1095.33,4958.33
XS Rating Curve= 0
Exp/Cntr=.5,.3

Type RM Length L Ch R = 1 ,31508.32,441.85,359.48,212.58
BEGIN DESCRIPTION:
lh5p86 - xs 1/4 at structure
Bank Station offset =     19714
XS extended on LOB
END DESCRIPTION:
XS GIS Cut Line= 6
 3196096.654363213928486.6231127     3195479.191    13928129.867
     3193979.644    13927357.094     3193464.463    13927044.305
      3191404.86    13925901.112     3190970.963    13925707.243
#Sta/Elev= 30
    -235   57.05   73.78   52.02  279.95   45.03  285.55   55.85  361.55   41.44
  447.55   37.94  495.55   33.03  540.55   23.93  600.55   22.43  642.55   19.03
  705.55    6.02  786.55    1.02  827.55   10.02  987.55   11.91 1110.55   19.91
 1255.55    22.9 1908.55   22.98 2206.55   29.98 3906.55   29.95 4148.55   42.35
 4205.55   55.74 4375.55   54.44 4528.07   41.56 4629.83   41.67  4683.6   42.02
 4728.15   51.09 4781.27   55.63 4903.72   58.89 5500.94   60.53 5599.02   57.24
#Mann= 3 ,-1 , 0
    -235     .99       0  285.55     .03       0 4375.55     .99       0
Bank Sta=600.55,4375.55
XS Rating Curve= 0
Exp/Cntr=.3,.1

Type RM Length L Ch R = 1 ,31148.84,3402.52,2283.1,887.74
BEGIN DESCRIPTION:
lh5p78
Bank Station offset =     19513
END DESCRIPTION:
XS GIS Cut Line= 6
     3196088.943    13927760.096     3195830.816    13927771.829
     3195525.757    13927677.965     3195220.698    13927525.435
     3191690.428     13925915.01     3191114.136    13925695.082
#Sta/Elev= 30
       0   57.35  208.12   55.84  298.23   53.18  367.66   49.55  455.73    47.7
  487.48   49.74  625.48   44.13  627.48   41.73  687.48   39.03  907.48    32.5
 1007.48   28.29 1047.48   25.49 1087.48   24.49 1265.48   20.88 1897.48   19.58
 2057.48   11.08 2217.48    8.08 3982.48   20.77 4318.48   25.37 4486.48   34.96
 4537.48   36.36 4609.48   43.35 4611.48   46.85 4637.48   49.05 4705.48   51.84
 4749.99   56.48  4913.9   59.29 5256.75   58.15 5379.04   60.54 5416.49   60.04
#Mann= 3 , 0 , 0
       0     .11       0  487.48     .03       0 4705.48     .11       0
Bank Sta=487.48,4705.48
XS Rating Curve= 0
Exp/Cntr=.3,.1

Type RM Length L Ch R = 1 ,28865.74,7234,5682.71,4652.21
BEGIN DESCRIPTION:
lh5p32
Bank Station offset =     18731
END DESCRIPTION:
XS GIS Cut Line= 6
     3197901.754    13923368.847     3197087.809    13923336.928
     3196846.675    13923330.857     3194154.931    13924463.134
     3191677.464    13925635.127       3190751.8    13925587.248
#Sta/Elev= 30
       0   63.69  822.26   62.29 1185.45    52.8 1257.14   48.92 1268.83   44.63
 1273.83   44.03 1274.83   41.33    1299   40.45 1588.83   26.43 1973.83   25.83
 2366.83   19.44 2788.83   16.54 3868.83   15.64 4373.83    8.54 4681.83   25.64
 4843.83   27.94 6038.83   30.24 6235.83   40.14 6391.83   42.04 6401.83   47.44
 6414.83   49.14 6477.83   51.84 6481.75    49.6 6603.36   56.31 6723.66   57.18
 6991.55   53.56 7247.69   59.22 7356.01    58.4 7500.41   53.39 7643.57   55.14
#Mann= 3 ,-1 , 0
       0     .11       0 1268.83     .03       0 6414.83     .11       0
Bank Sta=1299,6414.83
XS Rating Curve= 0
Exp/Cntr=.3,.1

Type RM Length L Ch R = 1 ,23183.03,1203.13,2019.39,2740.88
BEGIN DESCRIPTION:
lh4p39
Bank Station offset =     18174
END DESCRIPTION:
XS GIS Cut Line= 6
     3193736.268    13916075.256     3192603.128    13917367.993
     3192499.817    13917639.241     3188515.375    13922994.323
     3188006.729      13923783.8     3187416.219    13924422.189
#Sta/Elev= 30
       0   58.75  130.32   59.01     250   54.86  287.29   50.22  356.44   56.31
  692.62   59.48 1442.72   60.87 1811.02   56.75 1825.76   46.38 1834.76   45.68
    1845   41.18 1965.76   36.18 3175.76   29.37 6744.76   30.17 7143.76   26.67
 7237.76   22.37 7331.76   12.67 7519.76    1.57 7615.76   23.37 8375.76   25.37
 8545.76   28.27 8805.76   34.46 8925.76   40.66 9015.76   41.26 9026.76   48.86
 9046.76   49.96 9301.28   58.75 9455.12   61.22 9814.41   57.6410492.87   56.68
#Mann= 3 ,-1 , 0
       0     .11       0 1825.76     .03       0 9046.76     .11       0
Bank Sta=1965.76,9046.76
XS Rating Curve= 0
Exp/Cntr=.3,.1