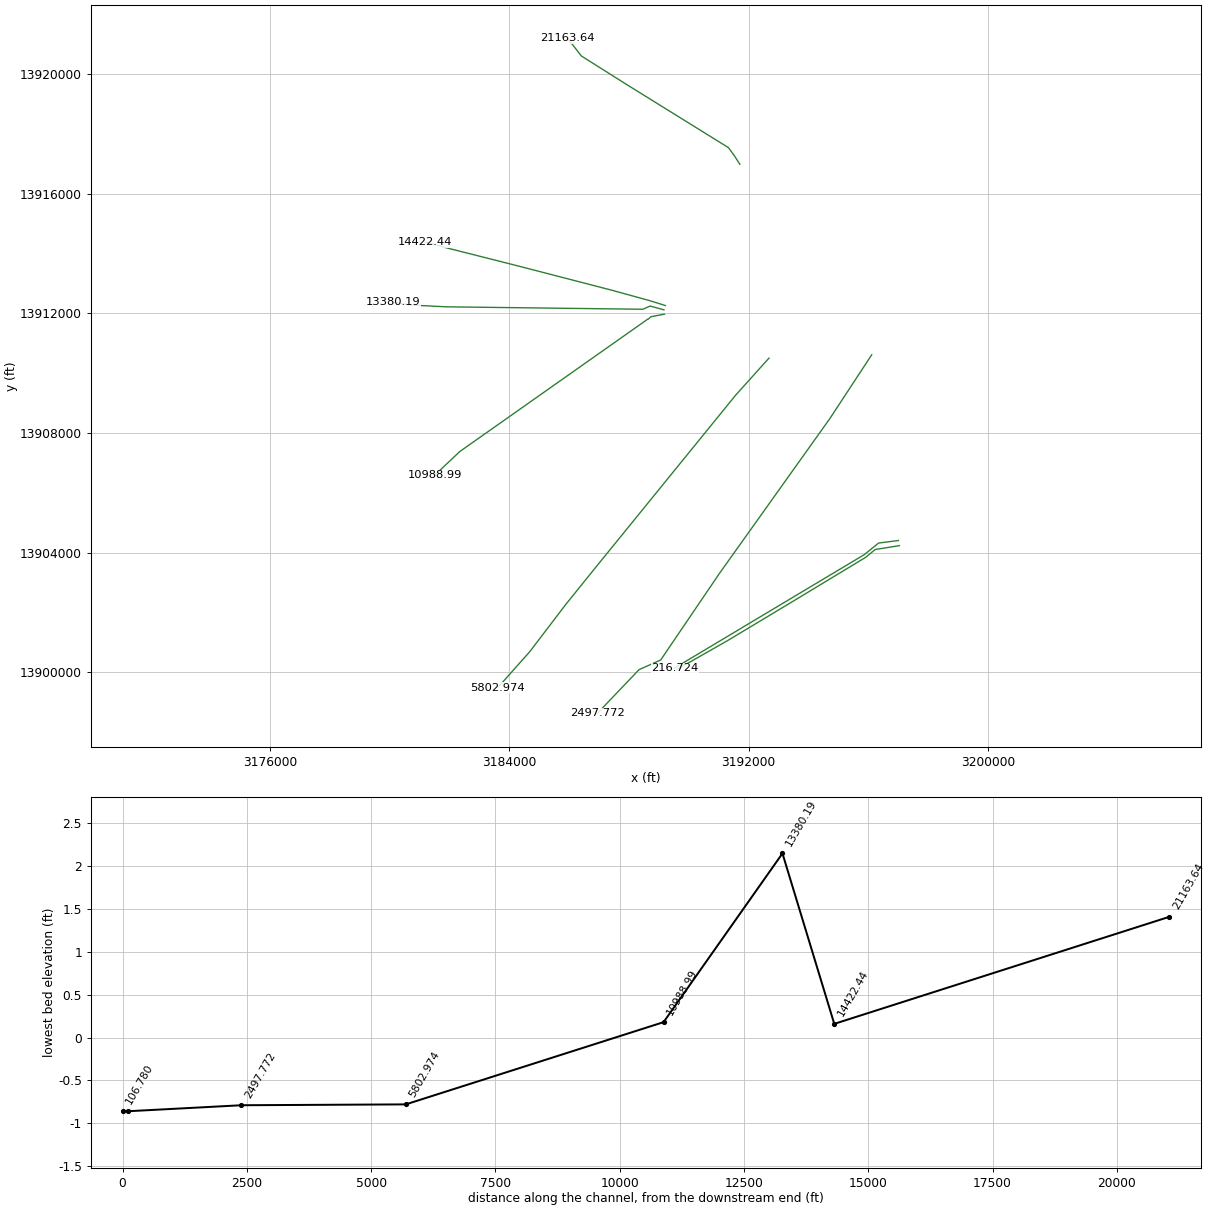
HEC-RAS study G103-00-00LH.prj: G103-00-00LH

--- G103-00-00LH.g02 (geometry) --- (continued)

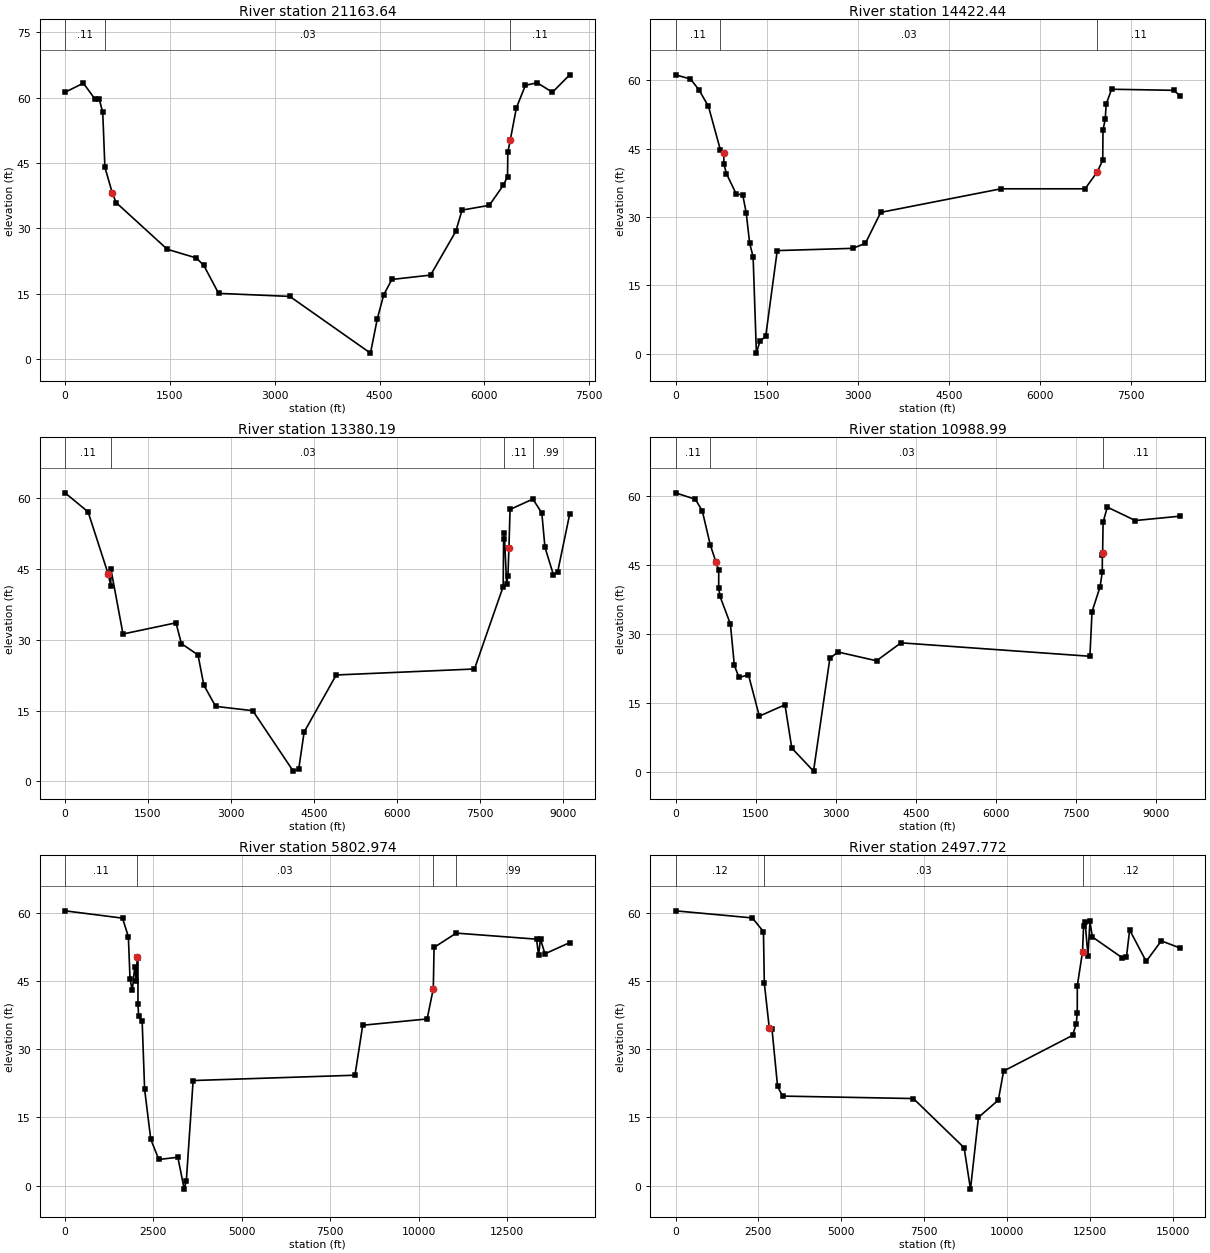
Type RM Length L Ch R = 1 ,21163.64,6211.41,6741.2,7366.64
BEGIN DESCRIPTION:
lh3p95
Bank Station offset =     19430
END DESCRIPTION:
XS GIS Cut Line= 6
     3191709.383     13916984.96      3191516.34    13917287.063
      3191326.35     13917543.55     3187920.247    13919655.208
     3186408.793    13920608.105     3185947.925    13921198.325
#Sta/Elev= 30
       0   61.21  262.25    63.3   427.2   59.68  489.81   59.59   539.5   56.65
  570.46   44.03  674.46   38.23  730.46   35.93 1462.46   25.22 1879.46   23.22
 1985.46   21.52 2197.46   15.11 3216.46   14.41 4370.46    1.41 4468.46    9.31
 4560.46    14.8 4676.46    18.3 5230.46    19.3 5590.46    29.3 5680.46    34.2
 6070.46   35.29 6270.46   39.88 6331.46   41.88 6335.46   47.48 6369.46   50.17
 6458.81   57.68 6587.59   62.81 6755.63   63.39 6974.18   61.21 7220.95   65.21
#Mann= 3 ,-1 , 0
       0     .11       0  570.46     .03       0 6369.46     .11       0
Bank Sta=674.46,6369.46
XS Rating Curve= 0
Exp/Cntr=.3,.1

Type RM Length L Ch R = 1 ,14422.44,503.78,1042.24,1725.38
BEGIN DESCRIPTION:
lh2p65
Bank Station offset =     19261
END DESCRIPTION:
XS GIS Cut Line= 6
     3189219.667    13912260.883     3188708.956     13912420.48
     3187423.822    13912774.672     3184176.564    13913614.813
     3181894.156    13914192.009     3181191.929    13914383.525
#Sta/Elev= 30
       0    61.2  245.01   60.29  384.55   57.94  542.68   54.26  739.09    44.7
  795.09   44.09   795.1   41.69  839.09   39.49  999.09   35.07 1106.09   34.87
 1163.09   30.97 1220.09   24.26 1277.09   21.26 1331.09     .16 1389.09    2.76
 1484.09    3.85 1674.09   22.65 2914.09   23.14 3124.09   24.23 3377.09   31.03
 5354.09    36.2 6739.09    36.2 6939.09   39.89 7030.09   42.48 7034.09   49.08
 7071.09   51.47 7086.73    54.8 7176.38   58.04 8199.65    57.8 8304.43   56.58
#Mann= 3 ,-1 , 0
       0     .11       0  739.09     .03       0 6939.09     .11       0
Bank Sta=795.09,6939.09
XS Rating Curve= 0
Exp/Cntr=.3,.1

Type RM Length L Ch R = 1 ,13380.19,806.05,2391.2,4287.54
BEGIN DESCRIPTION:
lh2p40
Bank Station offset =     19172
END DESCRIPTION:
XS GIS Cut Line= 6
     3189171.788    13912117.245     3188708.956    13912244.923
     3188466.458    13912136.821     3181902.019    13912218.359
     3180697.177    13912276.843 3180097.511974413912376.7858663
#Sta/Elev= 30
       0   61.17   417.1   57.13  779.95   43.96  827.64   41.44   828.2   45.09
  1048.2   31.23  2006.2    33.6  2104.2   29.19  2404.2   26.79  2510.2   20.38
  2723.2   15.88  3394.2   14.97  4126.2    2.15  4225.2    2.55  4323.2   10.44
  4903.2   22.54  7403.2   23.81  7922.2   41.29  7930.2   51.48  7942.2   52.68
  7984.4   41.91 8008.24   43.62    8026   49.37 8046.48   57.64 8459.24   59.85
    8621   56.88 8677.15   49.65 8830.85   43.77 8905.38    44.3    9125   56.67
#Mann= 4 ,-1 , 0
       0     .11       0   828.2     .03       0  7942.2     .11       0
 8459.24     .99       0
Bank Sta=779.95,8026
XS Rating Curve= 0
Exp/Cntr=.3,.1

Type RM Length L Ch R = 1 ,10988.99,4132.86,5186.02,5785.46
BEGIN DESCRIPTION:
lh1p99
Bank Station offset =     19198
END DESCRIPTION:
XS GIS Cut Line= 6
     3189187.748    13911973.608     3188732.929    13911886.624
     3188648.318    13911806.042     3188628.173    13911806.042
     3182341.028    13907377.209     3181495.163    13906579.223
#Sta/Elev= 30
       0   60.66  372.22   59.25  502.07   56.72  652.28    49.3     760   45.56
  809.28   43.89  809.28   39.98  833.28   38.18 1028.28   32.15 1102.28   23.14
 1190.28   20.53 1366.28   21.12 1570.28   12.12 2050.28    14.6 2178.28    5.19
 2585.28     .18 2891.28   24.67 3042.28   26.07 3765.28   24.16 4223.28   28.06
 7762.28   25.14 7802.28   34.84 7952.28   40.21 7994.28   43.41 7995.28    47.1
 8000.28    47.5 8009.17   54.28 8088.79   57.55 8612.72   54.64 9453.37   55.59
#Mann= 3 ,-1 , 0
       0     .11       0  652.28     .03       0 8000.28     .11       0
Bank Sta=760,8000.28
XS Rating Curve= 0
Exp/Cntr=.3,.1

Type RM Length L Ch R = 1 ,5802.974,3080.59,3305.2,3492.77
BEGIN DESCRIPTION:
lh1p11
Bank Station offset =     17959
END DESCRIPTION:
XS GIS Cut Line= 6
     3192683.283     13910503.48     3191565.746    13909260.456
     3186885.646    13903502.108     3185892.354    13902271.703
     3184687.107    13900690.087     3183616.028    13899485.325
#Sta/Elev= 30
       0   60.42 1626.51   58.81  1791.4   54.72 1838.66   45.42 1902.64    42.9
 1971.71   48.08 2014.98   44.97 2041.14   50.22 2063.14   50.11 2063.14   40.01
 2081.14    37.3 2181.14   36.19 2251.14   21.17 2425.14   10.16 2653.14    5.74
 3191.14    6.23 3371.14    -.78 3431.14    1.11 3623.14    23.1 8200.14   24.27
 8420.14   35.2610241.14   36.6410416.14   43.31 10437.7   52.3711063.76   55.52
 13337.1   54.1913392.06   50.6513447.79    54.213572.53   50.9614273.74   53.43
#Mann= 4 ,-1 , 0
       0     .11       0 2041.14     .03       010416.14     .11       0
11063.76     .99       0
Bank Sta=2041.14,10416.14
XS Rating Curve= 0
Exp/Cntr=.3,.1

Type RM Length L Ch R = 1 ,2497.772,3738.35,2281.05,1425.38
BEGIN DESCRIPTION:
lh0p47
Bank Station offset =     17320
Block added to ROB to prevent extension in cross-section
END DESCRIPTION:
XS GIS Cut Line= 6
     3196119.528    13910614.326     3194722.861    13908486.071
     3191031.792    13903309.503     3189061.736    13900406.391
     3188338.095    13900083.897     3186941.427    13898620.721
#Sta/Elev= 30
       0   60.44 2317.71   58.88 2653.82   55.86 2679.92   44.52 2829.92    34.6
 2909.92    34.5 3079.92   21.79 3229.92   19.68 7176.92   19.14 8707.92    8.32
 8899.92    -.79 9139.92      15 9739.92   18.79 9899.92   25.1911979.92   33.04
12089.92   35.5412121.92   38.0312122.92   43.9312279.92   51.4212312.53   57.19
12357.09      5812444.21   50.6112504.52   58.1112575.59    54.713477.74   50.11
13606.39   50.3213701.71   56.2314200.79   49.3214657.63   53.8315226.83   52.25
#Mann= 3 ,-1 , 0
       0     .12       0 2679.92     .03       012279.92     .12       0
#Block Obstruct= 2 , 0
       0                13739.23       0   56.27
Bank Sta=2829.92,12279.92
XS Rating Curve= 0
Exp/Cntr=.3,.1

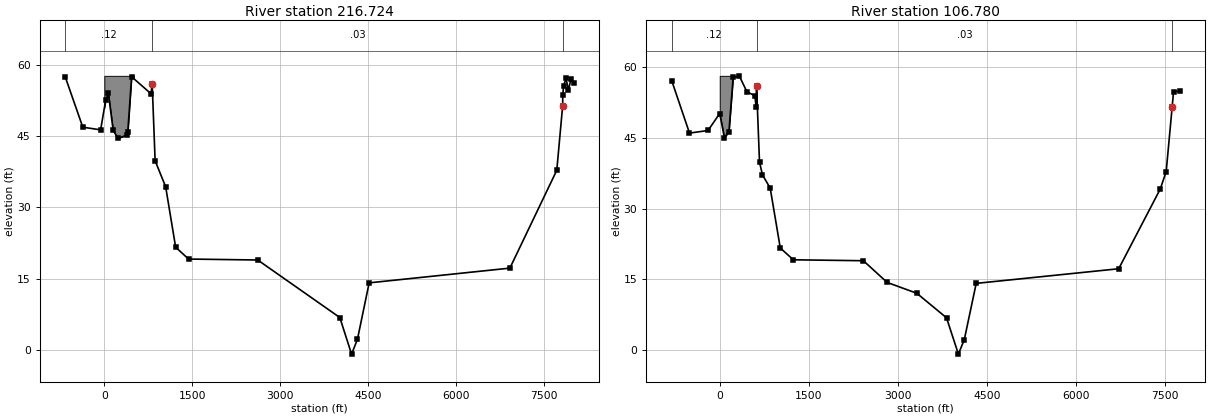
Type RM Length L Ch R = 1 ,216.724 ,106.74,109.94,134.26
BEGIN DESCRIPTION:
lh0p0196
Bank Station offset =     19184
XS extended on LOB
pond in LOB, hence blocked
END DESCRIPTION:
XS GIS Cut Line= 5
      3197012.12     13904402.71     3196348.797    13904317.292
     3195870.165    13903929.828     3189807.491    13900305.899
     3189533.987    13900134.959
#Sta/Elev= 30
 -667.04   57.51    -367    46.9     -63   46.34   22.35   52.54   68.66   54.03
  150.07   46.32  228.25   44.56  388.64   45.23  400.69   45.98   465.2   57.52
  796.12   53.94  816.16   56.05  866.16   39.85 1046.16   34.35 1216.16   21.65
 1436.16   19.15 2616.16   18.95 4016.16    6.84 4216.16    -.86 4316.16    2.24
 4516.16   14.14 6916.16   17.24 7716.16   37.84 7816.16   51.44  7817.5   53.71
 7833.34   55.62 7873.56   57.16 7914.98   54.73  7956.9   57.01 8001.54   56.16
#Mann= 3 , 0 , 0
 -667.04     .12       0  816.16     .03       0 7816.16     .12       0
#Block Obstruct= 2 , 0
       0  501.96   57.71               0
Bank Sta=816.16,7816.16
XS Rating Curve= 0
Exp/Cntr=.3,.1

Type RM Length L Ch R = 1 ,106.780 ,261.09,106.78,283.31
BEGIN DESCRIPTION:
lh0p0102
Bank Station offset =     19380
XS extended on LOB
This is the most d/s cross section. The flow lines extended beyond the limit of study and hence the LOB and ROB reach lengths > channel reach length
pond in LOB, hence blocked
END DESCRIPTION:
XS GIS Cut Line= 6
      3197041.79     13904230.98     3196234.837    13904100.768
     3195915.749     13903838.66     3193579.568    13902425.556
     3191296.127    13901052.772      3189605.93    13900091.376
#Sta/Elev= 30
 -809.19   57.14    -509      46    -197   46.55       0   50.15   78.53   45.04
  155.34   46.32  226.26   57.83  329.07   58.14  456.38    54.8  592.02    53.9
  613.65   51.52  620.23   56.04  670.23   39.84  720.23   37.14  850.23   34.34
 1020.23   21.64 1240.23   19.14 2420.23   18.94 2820.23   14.34 3320.23   12.04
 3820.23    6.84 4020.23    -.86 4120.23    2.24 4320.23   14.14 6720.23   17.24
 7420.23   34.14 7520.23   37.84 7620.23   51.44 7644.25    54.8 7752.88    54.9
#Mann= 3 , 0 , 0
 -809.19     .12       0  620.23     .03       0 7620.23     .12       0
#Block Obstruct= 2 , 0
       0  329.07   58.14               0
Bank Sta=620.23,7620.23
XS Rating Curve= 0
Exp/Cntr=.3,.1

Chan Stop Cuts=-1